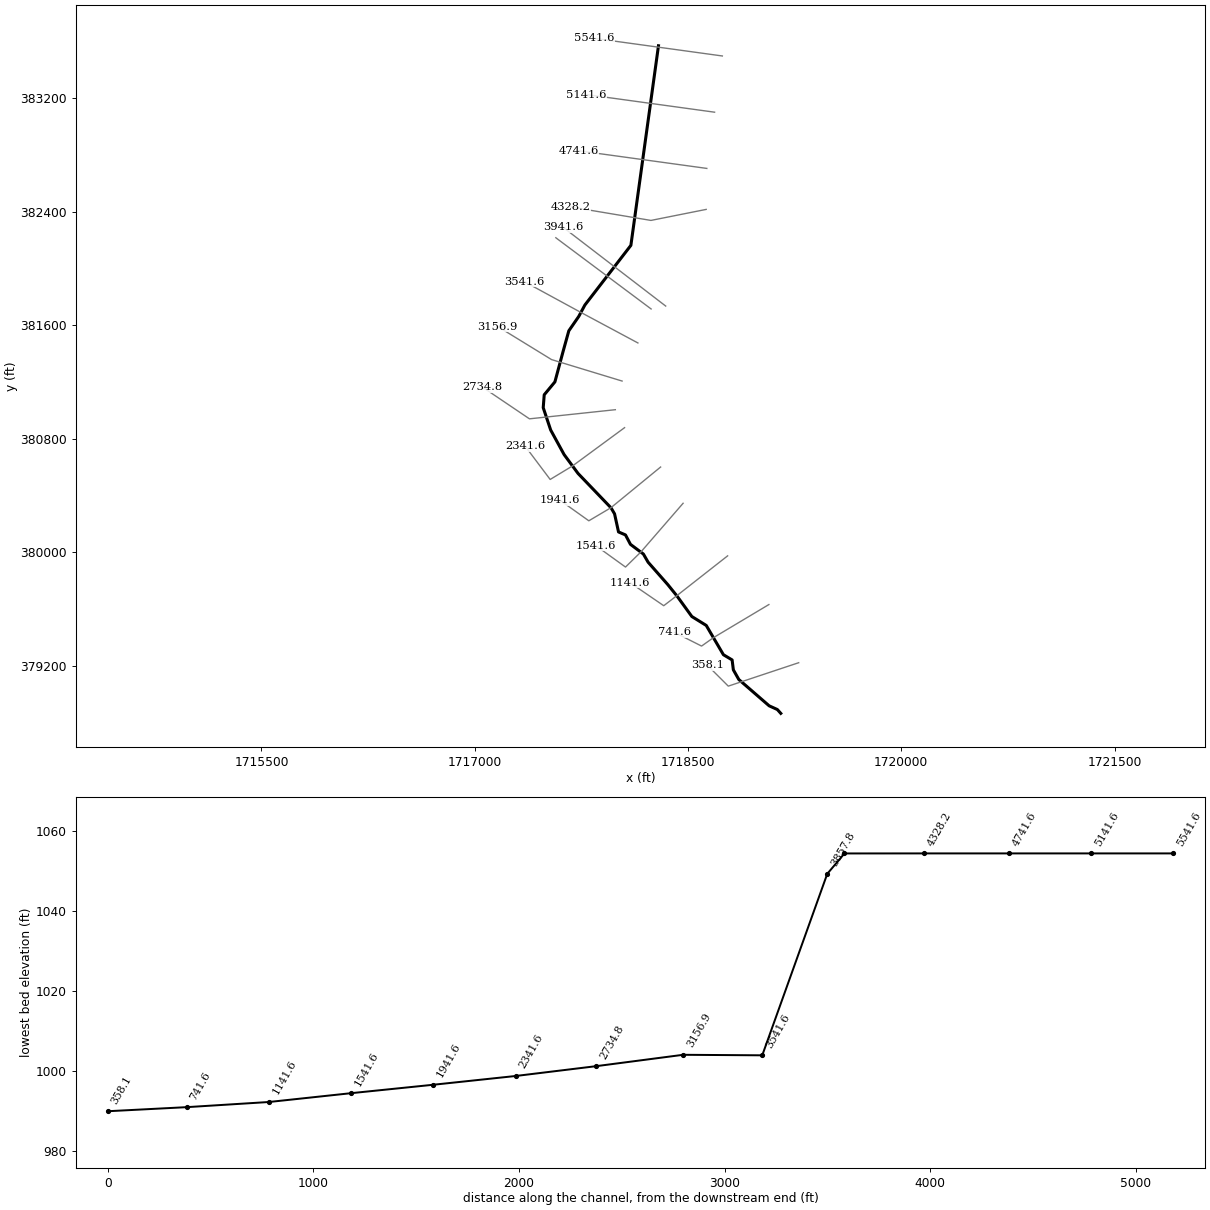
--- HbbsRn.prj (project) ---

Proj Title=HbbsRn
Current Plan=p01
Default Exp/Contr=0,0
English Units
Geom File=g01
Flow File=f01
Plan File=p01
BEGIN DESCRIPTION:
END DESCRIPTION:
DSS Export Rating Curves= 0
DSS Export Rating Curve Sorted= 0
DSS Export Volume Flow Curves= 0
DXF OffsetX= 0
DXF OffsetY= 0
DXF ScaleX= 0
DXF ScaleY= 0

--- HbbsRn.p01 (plan) ---

Plan Title=Floodplain
Program Version=4.00
Geom File=g01
Flow File=f01
K Sum by GR=0
Std Step Tol=0.01
Critical Tol=0.01
Num of Std Step Trials=20
Max Error Tol=0.3
Flow Tol Ratio=0.001
Split Flow NTrial=30
Split Flow Tol=0.02
Split Flow Ratio=0.02
Log Output Level=0
Friction Slope Method=1
Unsteady Friction Slope Method=2
Unsteady Bridges Friction Slope Method=1
Global Log Level=0
CheckData=False
Run HTab=0
Run UNet=0
Run PostProcess=0
UNET Theta=0
UNET Theta Warmup=0
UNET ZTol=0
UNET ZSATol=0
UNET MxIter=0
UNET MaxInSteps=0
UNET DtIC=0
UNET DtMin=0
UNET MaxCRTS=0
UNET WFStab=0
UNET SFStab=0
UNET WFX=0
UNET SFX=0
UNET DSS MLevel=0
UNET DZMax Abort=0
UNET Convert EG Bridges=0
UNET Use Existing IB Tables=0
UNET Froude Limit=0
UNET Froude Power=0
Write IC File=0
Echo Input=False
Echo Output=False
Write Detailed=0

--- HbbsRn.f01 (steady flow) ---

Flow Title=NFF Regression Equation
Program Version=4.00
Number of Profiles=1
Profile Names=P100yr
River Rch & RM=HbbsRn,Main      ,5541.6
759.9212
River Rch & RM=HbbsRn,Main      ,3941.6
788.5428
River Rch & RM=HbbsRn,Main      ,3941.6
870.4608
River Rch & RM=HbbsRn,Main      ,358.1
  961.42
Boundary for River Rch & Prof#=HbbsRn,Main      ,1
Up Type=0
Dn Type=3
Dn Slope=0.005854

--- HbbsRn.g01 (geometry) ---

Geom Title=USGS 3m DEM
Program Version=4.00

River Reach=HbbsRn          ,Main
Reach XY= 30
     1718292.398      383571.589     1718098.359      382164.808
     1717774.961      381744.391      1717731.75       381663.87
     1717661.826       381562.48      1717621.62      381417.388
     1717563.933      381202.372     1717488.765      381111.471
     1717481.773       381020.57     1717534.215      380863.242
     1717628.613       380690.18     1717726.506      380557.325
     1717959.003      380314.339     1717983.476      380272.385
     1718011.446      380144.774     1718060.392      380123.797
     1718095.354      380057.369     1718186.255      379989.194
     1718219.469      379931.506     1718357.569      379774.178
     1718422.248      379693.766     1718527.134      379548.674
     1718628.524      379485.742     1718749.142      379279.467
     1718810.325      379242.757     1718819.066      379172.833
     1718857.524      379104.657     1719070.792      378919.359
     1719128.479      378893.138     1719152.688      378866.048

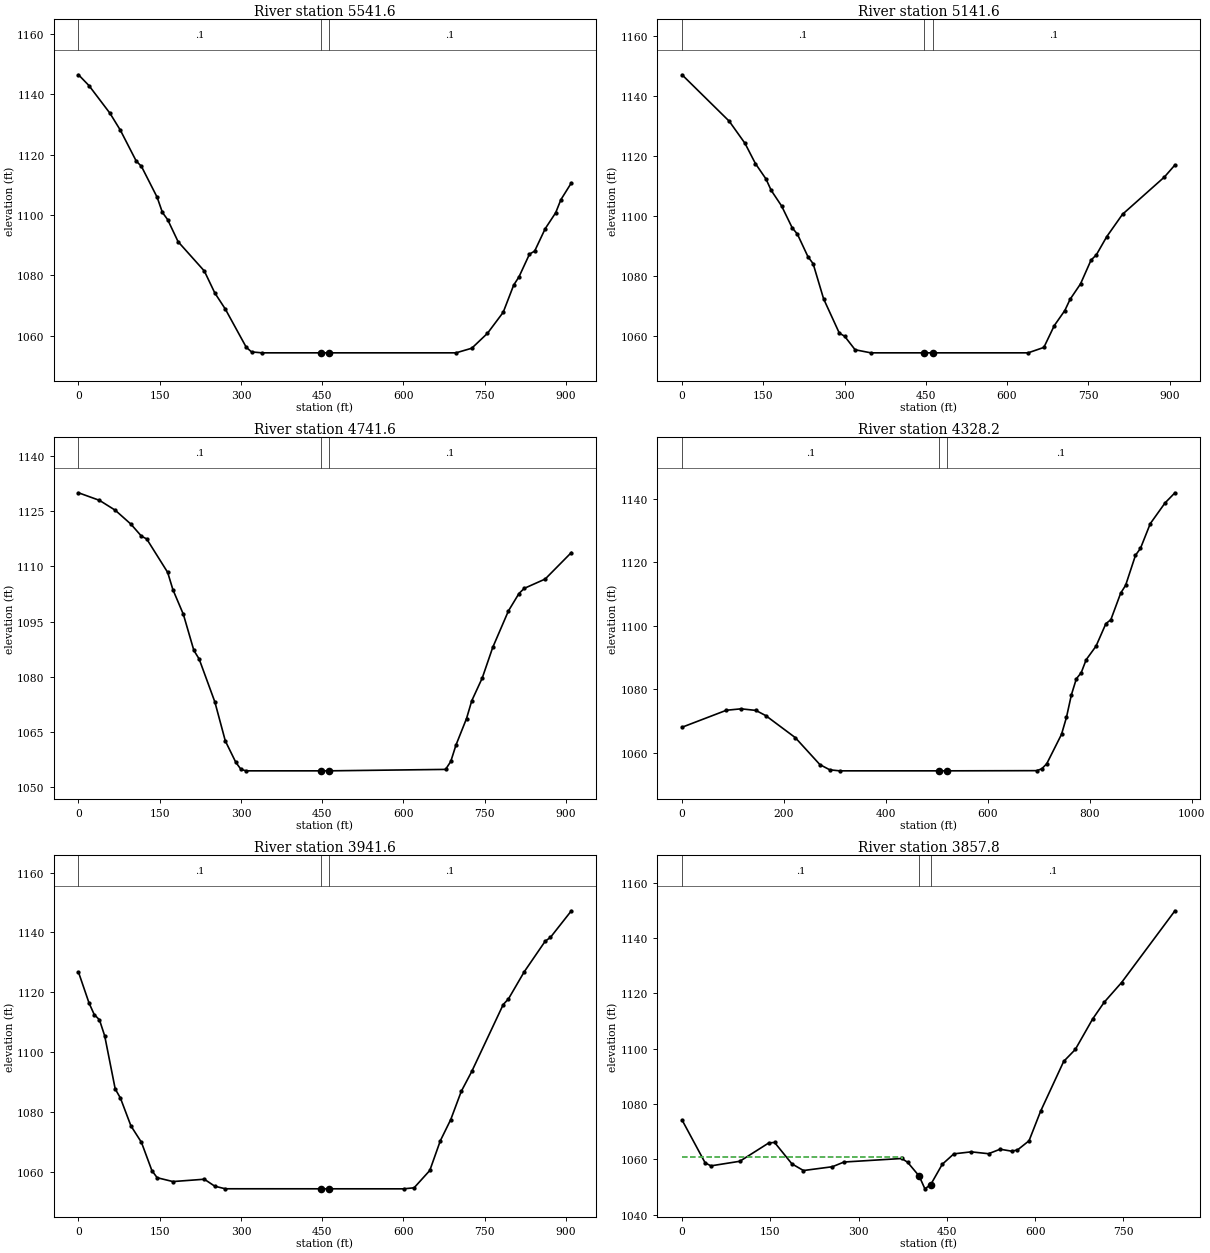
Type RM Length L Ch R = 1 ,5541.6  ,400,400,400
XS GIS Cut Line= 3
     1718741.764      383499.512     1718291.031      383561.682
     1717840.299      383623.853
#Sta/Elev= 30
       0 1146.44    19.4 1142.85    58.1  1133.7    77.4 1128.06   106.5  1117.9
   116.2 1116.12   145.2 1105.89   154.9 1100.87   164.6 1098.49   183.9 1091.18
   232.3 1081.48   251.7  1074.2   271.1 1068.87   309.8 1056.21   319.5  1054.7
   338.8 1054.39   447.5 1054.39   462.5 1054.39     697 1054.39   726.1 1055.92
   755.1 1060.86   784.1 1067.81   803.5 1076.83   813.2 1079.53   832.6 1087.06
   842.2 1088.08   861.6 1095.47     881 1100.77   890.6 1105.09     910 1110.67
#Mann= 3 , 0 , 0
       0      .1       0   447.5    .045       0   462.5      .1       0
Bank Sta=447.5,462.5
XS Rating Curve= 0 ,0
Exp/Cntr=0.3,0.1

Type RM Length L Ch R = 1 ,5141.6  ,400,400,400
XS GIS Cut Line= 3
     1718687.109      383103.264     1718236.376      383165.434
     1717785.644      383227.604
#Sta/Elev= 30
       0 1147.11    87.1 1131.63   116.2 1124.25   135.5 1117.49   154.9 1112.39
   164.6 1108.57   183.9 1103.33   203.3 1096.11     213 1093.96   232.3 1086.51
     242 1084.11   261.4 1072.37   290.4 1060.95   300.1 1059.94   319.5 1055.42
   348.5 1054.39   447.5 1054.39   462.5 1054.39   638.9 1054.39     668  1056.2
   687.3 1063.49   706.7  1068.5   716.4 1072.23   735.7 1077.39   755.1 1085.31
   764.8 1087.04   784.1 1093.13   813.2 1100.59   890.6 1113.03     910 1117.03
#Mann= 3 , 0 , 0
       0      .1       0   447.5    .045       0   462.5      .1       0
Bank Sta=447.5,462.5
XS Rating Curve= 0 ,0
Exp/Cntr=0.3,0.1

Type RM Length L Ch R = 1 ,4741.6  ,414.05,413.388,412.726
XS GIS Cut Line= 3
     1718632.454      382707.016     1718181.721      382769.186
     1717730.989      382831.356
#Sta/Elev= 30
       0 1130.04    38.7 1127.98    67.8  1125.3    96.8  1121.5   116.2 1118.24
   125.9 1117.48   164.6 1108.39   174.3 1103.68   193.6 1096.97     213 1087.15
   222.7 1084.83   251.7 1073.16   271.1 1062.51   290.4 1056.72   300.1 1054.76
   309.8 1054.39   447.5 1054.39   462.5 1054.39   677.7 1054.78   687.3 1056.94
     697 1061.44   716.4 1068.62   726.1 1073.47   745.4 1079.64   764.8 1087.98
   793.8 1097.91   813.2 1102.63   822.9 1104.03   861.6 1106.57     910 1113.79
#Mann= 3 , 0 , 0
       0      .1       0   447.5    .045       0   462.5      .1       0
Bank Sta=447.5,462.5
XS Rating Curve= 0 ,0
Exp/Cntr=0.3,0.1

Type RM Length L Ch R = 1 ,4328.2  ,397.888,386.612,375.336
XS GIS Cut Line= 3
      1718627.99      382418.157      1718239.54      382340.467
     1717676.334      382435.107
#Sta/Elev= 30
       0 1068.11      87 1073.45   115.9  1073.9   144.9  1073.4   164.3 1071.76
   222.2 1064.84   270.5 1056.35   289.9 1054.71   309.2 1054.39   504.5 1054.39
   519.5 1054.39   696.2 1054.45   705.9 1055.04   715.6 1056.61   744.6 1065.86
   754.3  1071.2     764  1078.3   773.7 1083.34   783.3 1085.27     793 1089.35
   812.4 1093.63   831.7  1100.7   841.4 1101.93   860.8 1110.32   870.4 1112.75
   889.8 1122.22   899.5 1124.36   918.8 1132.16   947.9  1138.7   967.2 1141.87
#Mann= 3 , 0 , 0
       0      .1       0   504.5    .045       0   519.5      .1       0
Bank Sta=504.5,519.5
XS Rating Curve= 0 ,0
Exp/Cntr=0.3,0.1

Type RM Length L Ch R = 1 ,3941.6  ,83.502,83.795,84.087
XS GIS Cut Line= 3
     1718343.218       381736.87     1717982.574      382014.289
     1717621.931      382291.707
#Sta/Elev= 30
       0 1126.73    19.4 1116.47      29 1112.59    38.7 1110.82    48.4 1105.44
    67.8 1087.72    77.4  1084.7    96.8 1075.41   116.2 1069.91   135.5 1060.48
   145.2  1058.1   174.3 1056.81   232.3 1057.59   251.7 1055.25   271.1  1054.4
   447.5 1054.39   462.5 1054.39   600.2 1054.38   619.6 1054.73   648.6 1060.52
     668 1070.43   687.3 1077.53   706.7 1086.94   726.1  1093.6   784.1 1115.91
   793.8 1117.81   822.9 1126.85   861.6 1137.07   871.3 1138.35     910 1147.24
#Mann= 3 , 0 , 0
       0      .1       0   447.5    .045       0   462.5      .1       0
Bank Sta=447.5,462.5
XS Rating Curve= 0 ,0
Exp/Cntr=0.3,0.1

Type RM Length L Ch R = 1 ,3857.8  ,312.818,316.205,319.444
XS GIS Cut Line= 3
      1718240.68      381716.359     1717572.207      382216.882
     1717570.544      382218.545
#Sta/Elev= 30
       0 1074.17    39.3 1058.65    49.1 1057.59    98.2 1059.25   147.4 1065.88
   157.2 1066.05   186.7  1058.3   206.3  1055.9   255.4 1057.27   275.1 1058.97
   373.3 1060.25   383.2 1058.89   402.8 1053.92   412.6 1049.28   422.5 1050.83
   442.1 1058.16   461.8 1061.93   491.2 1062.65   520.7 1061.98   540.4  1063.6
     560  1062.9   569.8 1063.32   589.5 1066.65   609.1  1077.3   648.4 1095.35
   668.1 1099.66   697.5 1110.65   717.2 1116.73   746.7 1123.85   837.4  1149.8
#Mann= 3 , 0 , 0
       0      .1       0   402.8    .045       0   422.5      .1       0
#XS Ineff= 2 , 0
           372.9 1060.71
Permanent Ineff=
       F       F
Bank Sta=402.8,422.5
XS Rating Curve= 0 ,0
Exp/Cntr=0.3,0.1

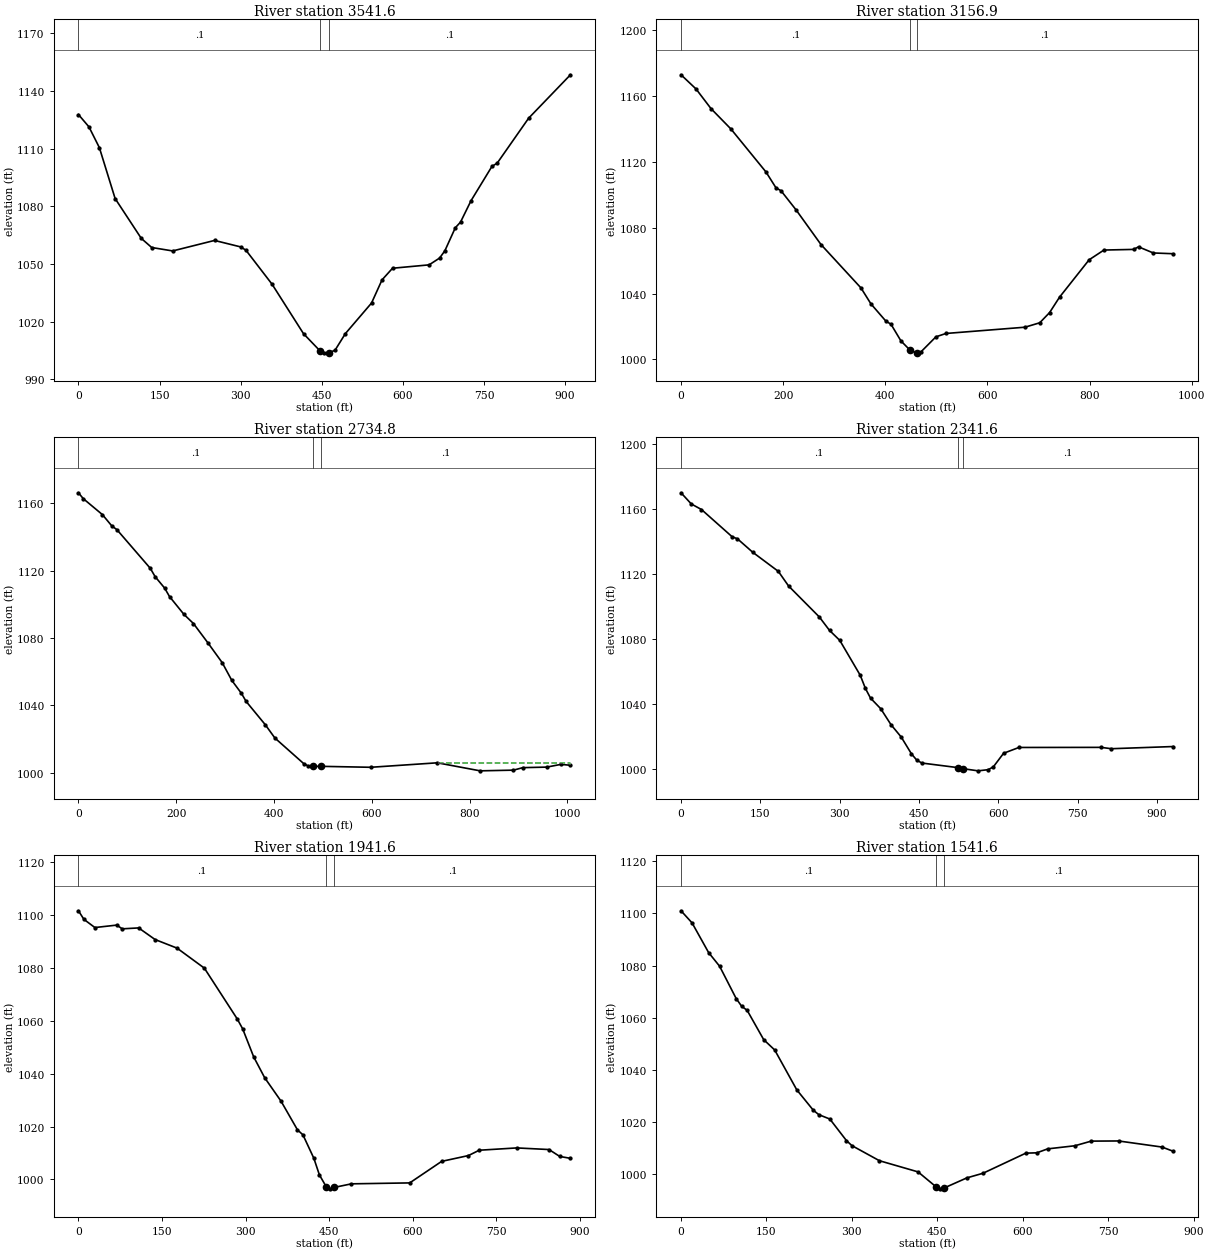
Type RM Length L Ch R = 1 ,3541.6  ,380.124,384.615,389.254
XS GIS Cut Line= 3
      1718147.75      381476.828     1717746.832      381691.973
      1717347.33      381909.768
#Sta/Elev= 30
       0 1127.77    19.4 1121.38    38.7 1110.56    67.8  1084.1   116.2 1063.37
   135.5 1058.62   174.3 1056.84   251.7  1062.3   300.1 1058.93   309.8 1057.21
   358.2 1039.49   416.3 1013.79   447.5 1004.65     455 1003.84   462.5 1003.91
   474.4 1005.12   493.7 1013.84   542.1 1029.75   561.5 1041.79   580.9 1047.84
   648.6  1049.6     668 1053.14   677.7 1056.91     697 1068.88   706.7 1071.85
   726.1 1082.96   764.8 1100.82   774.5  1102.5   832.6 1125.86     910 1148.46
#Mann= 3 , 0 , 0
       0      .1       0   447.5    .045       0   462.5      .1       0
Bank Sta=447.5,462.5
XS Rating Curve= 0 ,0
Exp/Cntr=0.3,0.1

Type RM Length L Ch R = 1 ,3156.9  ,412.78,422.172,431.565
XS GIS Cut Line= 3
     1718036.605      381208.331      1717540.33      381359.631
     1717161.592      381592.701
#Sta/Elev= 30
       0 1172.91    29.4 1164.29    58.7 1152.36    97.9 1139.92   166.4 1113.85
     186 1104.21   195.8 1102.46   225.2 1090.87   274.1 1069.77   352.4 1043.41
     372 1033.68   401.4 1023.16   411.1 1021.39   430.7 1011.21   447.7 1005.85
   460.1 1003.97   462.7 1004.13   469.9 1004.57   499.2  1013.7   518.8 1015.74
   673.5 1019.54   702.5 1022.23   721.8 1028.43   741.2 1037.77   799.2  1060.5
   828.2 1066.42   886.2 1066.81   895.9 1068.38   924.9 1064.65   963.5 1064.19
#Mann= 3 , 0 , 0
       0      .1       0   447.7    .045       0   462.7      .1       0
Bank Sta=447.7,462.7
XS Rating Curve= 0 ,0
Exp/Cntr=0.3,0.1

Type RM Length L Ch R = 1 ,2734.8  ,381.222,393.213,403.166
XS GIS Cut Line= 3
     1717989.038      381006.433      1717384.95      380942.048
     1717054.768      381165.407
#Sta/Elev= 30
       0 1166.26     9.8 1162.78      49 1153.29    68.6 1146.44    78.4 1144.43
     147 1121.37   156.8 1116.44   176.4  1109.6   186.2 1104.63   215.6 1094.09
   235.2  1088.6   264.6 1077.19     294 1065.36   313.6 1054.84   333.2 1047.17
   342.9 1042.34   382.1  1028.5   401.7 1020.62   460.5 1005.46   470.3 1003.94
   480.6 1003.81   495.6 1003.81   597.7 1003.24   733.9  1005.9   821.4 1001.13
   889.5 1001.54   908.9 1003.03   957.5 1003.34   986.7 1004.97  1006.1 1004.43
#Mann= 3 , 0 , 0
       0      .1       0   480.6    .045       0   495.6      .1       0
#XS Ineff= 2 , 0
                          735.12         1005.95
Permanent Ineff=
       F       F
Bank Sta=480.6,495.6
XS Rating Curve= 0 ,0
Exp/Cntr=0.3,0.1

Type RM Length L Ch R = 1 ,2341.6  ,398.825,400,399.71
XS GIS Cut Line= 4
     1718054.036      380879.848     1717687.735      380609.942
     1717530.619      380514.753     1717355.817      380747.823
#Sta/Elev= 30
       0  1170.1    19.4 1163.21    38.7 1159.77    96.8 1142.93   106.5 1141.76
   135.5 1133.44   183.9 1121.66   203.3 1112.63   261.4 1093.54   280.7 1085.24
   300.1 1079.09   338.8 1057.56   348.5  1049.5   358.2  1043.5   377.6 1036.93
   396.9 1027.12   416.3 1019.47   435.6 1009.12   445.3 1005.38     455 1003.48
   522.7 1000.67   532.3 1000.03   561.4  998.66   580.7  999.38   590.4 1001.13
   609.7 1009.49   638.7 1013.07   794.1 1013.13   813.5  1012.3     930 1013.64
#Mann= 3 , 0 , 0
       0      .1       0   522.7    .045       0   532.3      .1       0
Bank Sta=522.7,532.3
XS Rating Curve= 0 ,0
Exp/Cntr=0.3,0.1

Type RM Length L Ch R = 1 ,1941.6  ,394.935,400,406.445
XS GIS Cut Line= 4
      1718307.43      380602.424     1717957.857      380315.537
     1717802.543        380223.4     1717598.598      380369.084
#Sta/Elev= 30
       0 1101.47     9.8 1098.23    29.5 1095.14    68.8 1096.06    78.6 1094.65
   108.1    1095   137.6 1090.61     177 1087.37   226.1  1079.8   285.1 1060.63
   294.9 1056.87   314.6 1046.32   334.3 1038.45   363.7 1029.59   393.2 1018.76
   403.1 1016.85   422.7 1007.99   432.6 1001.75   444.7  997.33   452.2  996.47
   459.7  997.03   490.2  998.36   594.8  998.71   652.1 1006.84   700.3 1009.04
   719.6 1011.05     787 1011.92   844.9 1011.31   864.2  1008.7   883.4 1007.99
#Mann= 3 , 0 , 0
       0      .1       0   444.7    .045       0   459.7      .1       0
Bank Sta=444.7,459.7
XS Rating Curve= 0 ,0
Exp/Cntr=0.3,0.1

Type RM Length L Ch R = 1 ,1541.6  ,404.424,400,397.177
XS GIS Cut Line= 4
     1718465.609      380346.919     1718168.005      380002.881
      1718060.52      379897.349      1717851.09      380048.613
#Sta/Elev= 30
       0 1100.99    19.4 1096.34    48.4 1084.98    67.8 1079.71    96.8 1067.35
   106.5 1064.36   116.1 1062.82   145.2 1051.56   164.5 1047.61   203.3 1032.31
   232.3  1024.5     242  1022.8   261.3 1021.13   290.4 1012.88     300 1010.94
   348.4 1005.14   416.2 1000.86   447.4  995.21   454.9  994.36   462.4  994.73
     502  998.57   530.2 1000.33   605.5 1008.05   624.7 1008.17   643.8 1009.69
   691.6 1010.88   720.3 1012.66   768.2 1012.72   844.7 1010.38   863.9 1008.79
#Mann= 3 , 0 , 0
       0      .1       0   447.4    .045       0   462.4      .1       0
Bank Sta=447.4,462.4
XS Rating Curve= 0 ,0
Exp/Cntr=0.3,0.1

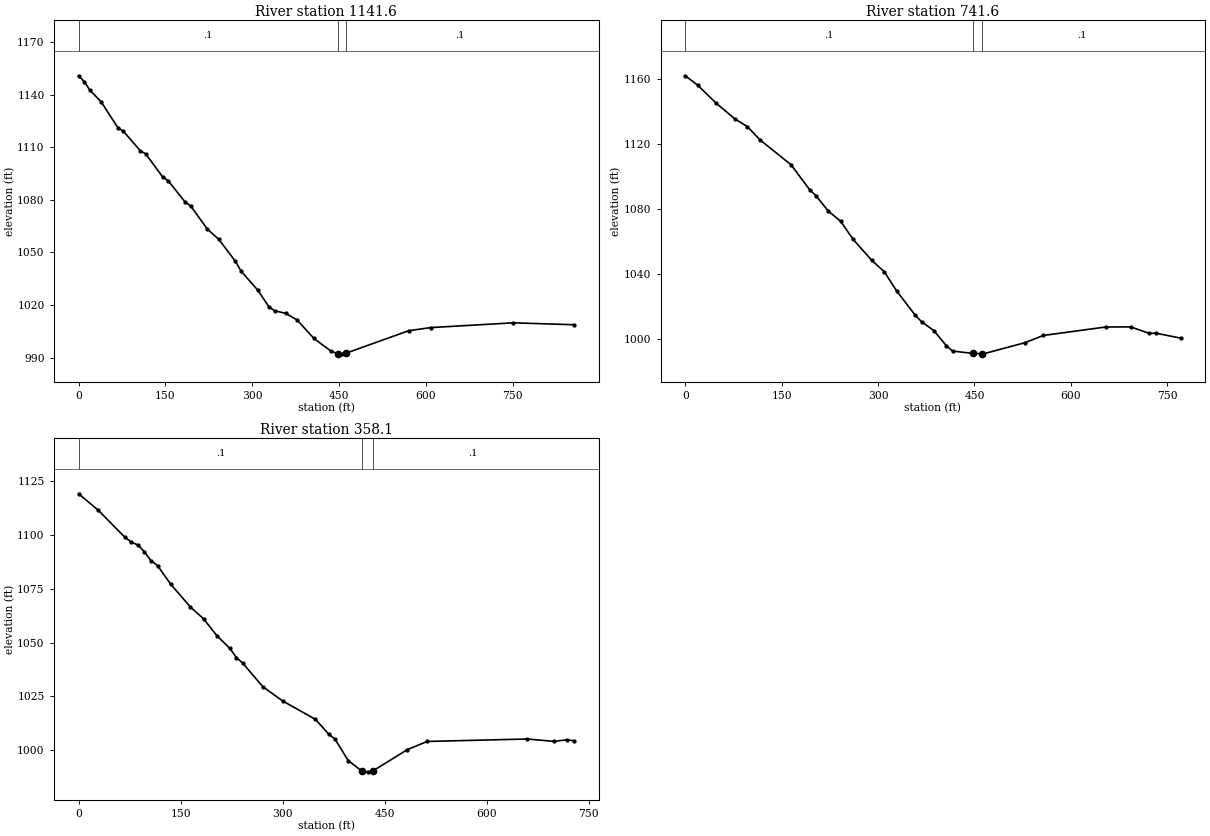
Type RM Length L Ch R = 1 ,1141.6  ,402.962,400,399.082
XS GIS Cut Line= 4
     1718778.793      379976.335     1718421.044      379695.263
      1718329.38       379624.91     1718093.871      379786.409
#Sta/Elev= 30
       0 1150.82     9.7 1147.52    19.4 1142.59    38.7 1136.06    67.8 1121.23
    77.4 1119.11   106.5 1108.12   116.2 1106.15   145.2 1093.13   154.9 1090.88
   183.9 1078.86   193.6 1076.56   222.6 1063.29     242 1057.57     271 1044.97
   280.7 1039.38   309.8 1028.43   329.1 1018.87   338.8 1016.77   358.2  1015.2
   377.5 1011.52   406.6 1000.95   435.6  993.83   447.5  992.25     455  992.15
   462.5  992.56   570.5 1005.35   608.6 1007.13   751.4 1009.85   856.1 1008.76
#Mann= 3 , 0 , 0
       0      .1       0   447.5    .045       0   462.5      .1       0
Bank Sta=447.5,462.5
XS Rating Curve= 0 ,0
Exp/Cntr=0.3,0.1

Type RM Length L Ch R = 1 ,741.6   ,390.577,383.436,374.38
XS GIS Cut Line= 4
     1719069.006      379633.072     1718678.857      379399.664
     1718595.554      379340.396     1718404.631      379436.805
#Sta/Elev= 30
       0 1162.21    19.3 1156.39    48.4 1145.18    77.4 1135.55    96.7 1130.87
   116.1 1122.74   164.4 1107.47   193.5 1091.98   203.1 1088.38   222.5 1078.87
   241.8  1072.5   261.2 1061.37   290.2 1048.43   309.5 1041.51   328.9 1029.62
   357.9 1014.58   367.6 1010.69   386.9  1005.1   406.3  995.84   415.9  992.56
   447.1  991.15   462.1  990.89   463.9  990.86     529  997.79   556.9 1002.18
   654.1 1007.39     693 1007.47   722.1 1003.47   731.9 1003.61   770.8 1000.55
#Mann= 3 , 0 , 0
       0      .1       0   447.1    .045       0   462.1      .1       0
Bank Sta=447.1,462.1
XS Rating Curve= 0 ,0
Exp/Cntr=0.3,0.1

Type RM Length L Ch R = 1 ,358.1   ,347.75,358.116,368.483
XS GIS Cut Line= 3
     1719278.644      379223.157      1718783.37      379058.066
     1718637.701      379203.735
#Sta/Elev= 30
       0 1119.21      29 1111.51    67.7  1099.1    77.3  1096.7      87 1095.44
    96.7 1092.25   106.3 1088.07     116  1085.8   135.3 1077.17   164.4 1066.49
   183.7 1061.03     203 1053.27   222.4 1047.23     232 1043.02   241.7 1040.25
   270.7 1029.47   299.7 1022.86     348 1014.28   367.4 1007.48     377 1004.98
   396.4  995.03   417.2  990.01   425.4  989.84   432.2   990.2   483.4 1000.21
   512.4 1003.98   659.4 1005.12   698.6 1004.01   718.3 1004.77   728.1 1004.26
#Mann= 3 , 0 , 0
       0      .1       0   417.2    .045       0   432.2      .1       0
Bank Sta=417.2,432.2
XS Rating Curve= 0 ,0
Exp/Cntr=0.3,0.1

Chan Stop Cuts=-1
Use User Specified Reach Order=0